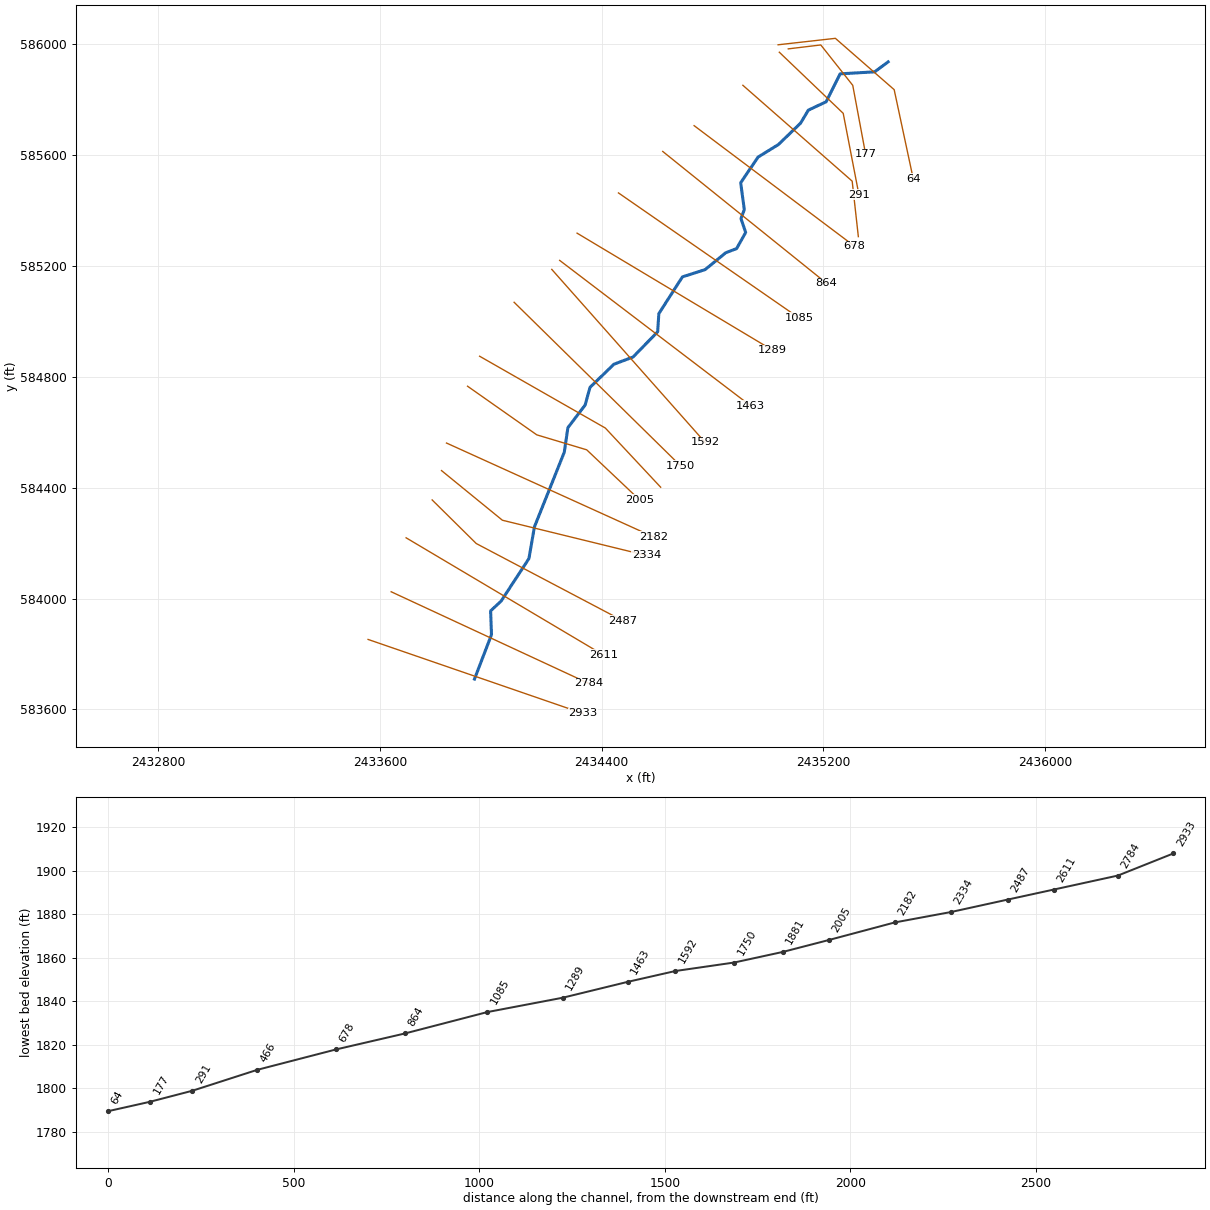
--- SBPOTOMC_T4.prj (project) ---

Proj Title=SBPOTOMC_T4
Current Plan=p01
Default Exp/Contr=0,0
English Units
Geom File=g01
Flow File=f01
Plan File=p01
BEGIN DESCRIPTION:
Stream Name: South Branch Potomac  Tributary 4
Flood Zone: Approximate
Pendleton County, West Virginia
HEC-RAS Version: 5.0.7
Hydrology Method:
Regression
END DESCRIPTION:
DSS File=dss
DSS Export Rating Curves= 0
DSS Export Rating Curve Sorted= 0
DSS Export Volume Flow Curves= 0
DXF OffsetX= 0
DXF OffsetY= 0
DXF ScaleX= 0
DXF ScaleY= 0

--- SBPOTOMC_T4.p01 (plan) ---

Plan Title=Floodplain
Program Version=5.07
Short Identifier=Floodplain
Geom File=g01
Flow File=f01
Subcritical Flow
K Sum by GR= 0
Std Step Tol= 0.01
Critical Tol= 0.01
Num of Std Step Trials= 20
Max Error Tol= 0.3
Flow Tol Ratio= 0.001
Split Flow NTrial= 30
Split Flow Tol= 0.02
Split Flow Ratio= 0.02
Log Output Level= 0
Friction Slope Method= 1
Unsteady Friction Slope Method= 2
Unsteady Bridges Friction Slope Method= 1
Parabolic Critical Depth
Global Vel Dist= 0 , 0 , 0
Global Log Level= 0
CheckData=True
Encroach Param=-1 ,0,0, 0
Computation Interval=0.1SEC
Output Interval=1MIN
Instantaneous Interval=Max Profile
Mapping Interval=1HOUR
Computation Time Step Use Courant=        0
Computation Time Step Use Time Series=    0
Computation Time Step Count To Double=0
Computation Time Step Max Doubling=0
Computation Time Step Max Halving=0
Computation Time Step Residence Courant=0
Run HTab= 0
Run UNet= 0
Run Sediment= 0
Run PostProcess= 0
Run WQNet= 0
Run RASMapper= 0
UNET Theta= 0
UNET Theta Warmup= 0
UNET ZTol= 0
UNET ZSATol= 0
UNET MxIter= 0
UNET Max Iter WO Improvement= 0
UNET MaxInSteps= 0
UNET DtIC= 0
UNET DtMin= 0
UNET MaxCRTS= 0
UNET WFStab= 0
UNET SFStab= 0
UNET WFX= 1
UNET SFX= 1
UNET 1D Methodology=Finite Difference
UNET DSS MLevel= 1
UNET Pardiso=0
UNET DZMax Abort= 0
UNET Use Existing IB Tables= 0
UNET Froude Reduction=False
UNET Froude Limit= 0
UNET Froude Power= 0
UNET D1 Cores= 0
UNET D2 Coriolis=0
UNET D2 Cores= 0
UNET D2 Theta= 1
UNET D2 Theta Warmup= 1
UNET D2 Z Tol= 0.01
UNET D2 Volume Tol= 0.01
UNET D2 Max Iterations= 20
UNET D2 Equation= 0
UNET D2 RampUpFraction=0.1
UNET D2 TimeSlices= 1
UNET D2 BCVolumeCheck=0
UNET D1D2 MaxIter= 0
UNET D1D2 ZTol=0.01
UNET D1D2 QTol=0.1
UNET D1D2 MinQTol=1
DSS File=dss
Write IC File= 0
Write IC File at Fixed DateTime=0
Write IC File at Sim End=0
Echo Input=False
Echo Parameters=False
Echo Output=False
Write Detailed= 0
HDF Write Warmup=0
HDF Write Time Slices=0
HDF Flush=0
HDF Face Node Velocities=0
HDF Compression= 1
HDF Chunk Size= 1
HDF Spatial Parts= 1
HDF Use Max Rows=0
HDF Fixed Rows= 1
Calibration Method= 0
Calibration Iterations= 20
Calibration Max Change=0.05
Calibration Tolerance=0.2
Calibration Maximum=1.5
Calibration Minimum=0.5
Calibration Optimization Method= 1
WQ AD Non Conservative
WQ ULTIMATE=-1
WQ Max Comp Step=1HOUR
WQ Output Interval=15MIN
WQ Output Selected Increments= 0
WQ Output face flow=0
WQ Output face velocity=0
WQ Output face area=0
WQ Output face dispersion=0
WQ Output cell volume=0
WQ Output cell surface area=0
WQ Output cell continuity=0
WQ Output cumulative cell continuity=0
WQ Output face conc=0
WQ Output face dconc_dx=0
WQ Output face courant=0
WQ Output face peclet=0
WQ Output face adv mass=0
WQ Output face disp mass=0
WQ Output cell mass=0
WQ Output cell source sink temp=0
WQ Output nsm pathways=0
WQ Output nsm derived pathways=0
WQ Output MaxMinRange=-1
WQ Daily Max Min Mean=-1
WQ Daily Range=0
WQ Daily Time=0
WQ Create Restart=0
WQ Fixed Restart=0
WQ System Summary=0
WQ Write To DSS=0
WQ Use Fixed Temperature=0
Sorting and Armoring Iterations= 10
XS Update Threshold= 0.02
Bed Roughness Predictor= 0
Hydraulics Update Threshold= 0.02
Energy Slope Method= 1
Volume Change Method= 1
Sediment Retention Method= 0
XS Weighting Method= 0
Number of US Weighted Cross Sections= 1
Number of DS Weighted Cross Sections= 1
Upstream XS Weight=0
Main XS Weight=1
Downstream XS Weight=0
Number of DS XS's Weighted with US Boundary= 1
Upstream Boundary Weight= 1
Weight of XSs Associated with US Boundary= 0
Number of US XS's Weighted with DS Boundary= 1
Downstream Boundary Weight= 0.5
Weight of XSs Associated with DS Boundary= 0.5
Percentile Method= 0
Sediment Output Level= 3
Mass or Volume Output= 0
Output Increment Type= 1
Profile and TS Output Increment= 1
XS Output Flag= 0
XS Output Increment= 10
Write Gradation File= 0
Read Gradation Hotstart= 0
Write HDF5 File= 1
Write Binary Output= 1
Write DSS Sediment File= 0
SV Curve= 0
Specific Gage Flag= 0

--- SBPOTOMC_T4.f01 (steady flow) ---

Flow Title=Flows
Program Version=5.07
Number of Profiles= 6
Profile Names=P100yr,P10yr,P25yr,P50yr,P500yr,P101yr
River Rch & RM=SBPOTOMC2_T1,Main            ,2933
     424     199     281     350     620     516
River Rch & RM=SBPOTOMC2_T1,Main            ,1750
     708     330     467     584    1040     862
River Rch & RM=SBPOTOMC_T4,Main            ,2933
     424     199     281     350     620     516
River Rch & RM=SBPOTOMC_T4,Main            ,1750
     708     330     467     584    1040     862
Boundary for River Rch & Prof#=SBPOTOMC_T4,Main            , 1
Up Type= 0
Dn Type= 3
Dn Slope=0.04382
Boundary for River Rch & Prof#=SBPOTOMC_T4,Main            , 2
Up Type= 0
Dn Type= 3
Dn Slope=0.04382
Boundary for River Rch & Prof#=SBPOTOMC_T4,Main            , 3
Up Type= 0
Dn Type= 3
Dn Slope=0.04382
Boundary for River Rch & Prof#=SBPOTOMC_T4,Main            , 4
Up Type= 0
Dn Type= 3
Dn Slope=0.04382
Boundary for River Rch & Prof#=SBPOTOMC_T4,Main            , 5
Up Type= 0
Dn Type= 3
Dn Slope=0.04382
Boundary for River Rch & Prof#=SBPOTOMC_T4,Main            , 6
Up Type= 0
Dn Type= 3
Dn Slope=0.04382
DSS Import GetInterval= 0
DSS Import GetPeak= 0
DSS Import FillOption= 0

--- SBPOTOMC_T4.g01 (geometry) ---

Geom Title=Geometry
Program Version=5.07

River Reach=SBPOTOMC_T4     ,Main
Reach XY= 30
2433941.54200003583709.5560000092434002.84900004583869.430999994
     2433999.699 583955.429000022434037.33000004583990.325000018
2434137.90419075584144.1479046492434157.71300003584258.292000011
2434265.43100002584527.7099999932434278.44600004584616.251000017
2434340.66600001584697.9159999942434358.27300003 584761.71100001
2434444.66181684584845.2199159862434513.46771762584871.130465582
2434602.32600003584962.176000014     2434606.544585027.721000016
2434691.60000002585160.2619999952434773.53465117585186.497723042
2434848.22729162585247.4924052032434886.99509807585262.224171657
2434919.81850754585320.6343333862434902.82180819585370.476575477
     2434914.873585402.9549999982434901.79100001585499.831000015
2434964.48800004585592.4070000052435037.89500001585637.637000009
2435117.88900003 585714.858000012435145.80899999585761.680999994
     2435210.243585792.0230000022435260.58000001585892.738000005
2435385.02600002585899.9120000152435433.73540697585935.931879357

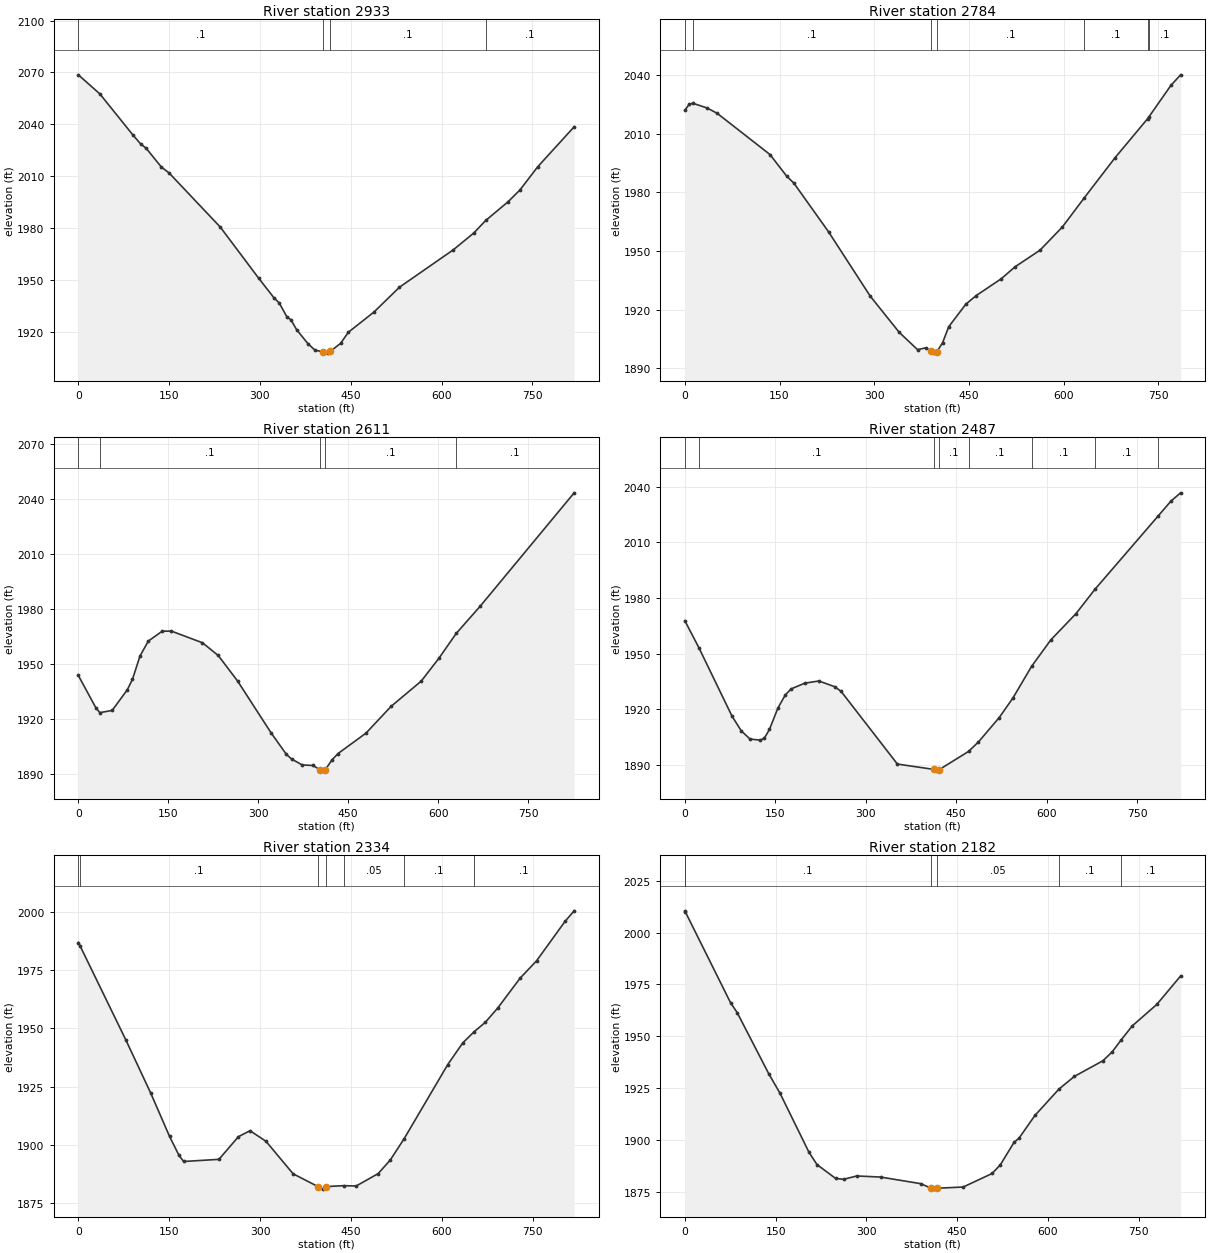
Type RM Length L Ch R = 1 ,2933    ,150.6,149.6,148.5
XS GIS Cut Line= 3
     2433557.625       583852.38     2433944.799      583719.011
     2434331.971      583585.642
#Sta/Elev= 30
       0 2068.64    35.7 2057.57    90.7 2033.66   103.3 2028.59   111.8 2026.34
   137.2 2015.37   149.9 2011.98   234.5 1980.71   297.9 1951.17   322.8 1940.02
   331.8 1936.92   344.5 1928.88   351.1 1927.21   360.5  1921.5   379.4 1913.33
     391 1909.58   403.7 1908.77   412.1 1907.92   416.4 1908.99   433.3 1913.59
     446 1919.97   488.3 1931.64   530.4 1945.98   619.4 1967.59   653.2 1977.29
   672.9 1984.53   709.8 1995.32   729.4 2002.12     759 2015.62     819 2038.64
#Mann= 4 ,-1 , 0
       0      .1       0   403.7    .045       0   416.4      .1       0
   672.9      .1       0
Bank Sta=403.7,416.4
XS Rating Curve= 0 ,0
Exp/Cntr=0.3,0.1

Type RM Length L Ch R = 1 ,2784    ,173.1,172.5,171.2
XS GIS Cut Line= 2
2433640.89092248584024.4002526632434353.18161157583693.769611568
#Sta/Elev= 30
       0    2022     7.1 2025.19   13.012025.634    35.5 2023.22    51.2 2020.53
   134.9 1999.41   161.4 1988.34   172.6 1984.85   227.6 1959.89   293.7 1926.92
   339.6 1908.39   368.7 1899.52   381.9 1900.48   390.4 1898.64   395.1 1897.75
   399.5 1898.57   408.4 1903.15   417.9 1911.21     445 1922.77   461.3 1927.16
     501 1935.78   523.3 1941.99   562.5 1950.42     598 1962.32  631.981976.941
   681.7 1997.88   732.92017.703  735.142018.718   769.9  2034.8   785.3 2040.21
#Mann= 7 ,-1 , 0
       0      .1       0   13.01      .1       0   390.4    .045       0
   399.5      .1       0  631.98      .1       0   732.9      .1       0
  735.14      .1       0
Bank Sta=390.4,399.5
XS Rating Curve= 0 ,0
Exp/Cntr=0.3,0.1

Type RM Length L Ch R = 1 ,2611    ,124.1,124,124.6
XS GIS Cut Line= 2
2433694.85411649584218.9973203452434405.84711649583796.728320345
#Sta/Elev= 30
       0 1943.55      29 1926.06   35.771923.255    56.4 1924.46    81.6  1935.7
    90.3 1941.46   102.9 1954.22   116.8 1962.34   139.9 1967.72   155.3 1967.75
     207  1961.4   233.3 1954.45   265.7 1940.47   321.5  1912.2   347.1 1900.42
   355.9 1897.88   373.4 1894.71   391.3 1894.41   402.6 1892.18   409.9 1891.33
   412.1 1892.21     423 1897.46   433.2 1900.94   479.7 1912.06   521.6 1926.68
   571.9 1940.48   601.7 1953.09  630.141966.463   670.4 1981.43   826.9 2043.24
#Mann= 5 ,-1 , 0
       0      .1       0   35.77      .1       0   402.6    .045       0
   412.1      .1       0  630.14      .1       0
Bank Sta=402.6,412.1
XS Rating Curve= 0 ,0
Exp/Cntr=0.3,0.1

Type RM Length L Ch R = 1 ,2487    ,151.5,153.3,155.5
XS GIS Cut Line= 3
2433788.75412633 584355.661980722433947.87390232584198.366389873
     2434477.439      583919.402
#Sta/Elev= 30
       0 1967.77   23.211953.302    78.2 1916.39    93.6 1908.46   108.1 1904.01
   125.1 1903.42   131.9 1904.47   140.4 1909.19   154.5 1920.76   166.7 1927.75
   176.3 1931.01   199.1 1934.11   222.4 1935.27     249 1932.15   259.3 1929.64
   352.6 1890.53   414.11887.613   417.5 1886.73   422.21887.591  470.521897.323
   486.9 1902.41   521.5 1915.59   544.1 1926.07   575.31943.242     607 1957.39
   648.7 1971.52  680.071984.589  784.842024.057   806.2 2032.13   822.3  2036.6
#Mann= 8 ,-1 , 0
       0      .1       0   23.21      .1       0   414.1    .045       0
   422.2      .1       0  470.52      .1       0   575.3      .1       0
  680.07      .1       0  784.84      .1       0
Bank Sta=414.1,422.2
XS Rating Curve= 0 ,0
Exp/Cntr=0.3,0.1

Type RM Length L Ch R = 1 ,2334    ,152.5,151.3,148.7
XS GIS Cut Line= 3
2433822.56077686584461.5078449512434042.20803849584282.382729903
     2434561.807      584155.194
#Sta/Elev= 30
       0  1986.9    2.86 1985.46    78.4 1945.08   119.7 1922.12   150.6 1903.61
   166.1 1895.54   173.8 1892.87   232.1 1893.79   264.2 1903.52   283.4 1906.09
   309.7 1901.55   354.5 1887.59   395.7 1882.07   395.7 1882.06     404    1881
   408.1 1882.09  438.181882.486   458.6 1882.34   494.9 1887.67   514.8 1893.47
  537.811902.674   609.8 1934.51   634.5 1943.78  653.361948.604   671.6  1952.6
   692.2 1958.76   729.2  1971.6   756.3 1979.03   803.4    1996   818.4 2000.51
#Mann= 7 ,-1 , 0
       0      .1       0    2.86      .1       0   395.7    .045       0
   408.1      .1       0  438.18     .05       0  537.81      .1       0
  653.36      .1       0
Bank Sta=395.7,408.1
XS Rating Curve= 0 ,0
Exp/Cntr=0.3,0.1

Type RM Length L Ch R = 1 ,2182    ,176.5,177.6,179.2
XS GIS Cut Line= 2
     2433840.493      584560.921     2434586.374      584222.655
#Sta/Elev= 30
       0 2010.54     .722010.145    75.6 1966.17    86.5 1961.43     139 1931.73
   157.2 1922.54   205.1 1894.02   218.3 1888.09     249 1881.41   262.2 1880.95
   284.1 1882.57   323.3 1882.05   389.6 1878.86   407.1 1876.65   411.5 1876.22
     417 1876.65   459.8 1877.24   507.7 1883.77   521.3    1888   543.9 1898.81
   552.1 1900.83   578.4  1911.8  618.181924.549   643.6 1930.64   690.6 1938.17
   705.8 1942.43  721.091948.344     739 1954.97   779.6 1965.36     819 1979.09
#Mann= 6 ,-1 , 0
       0      .1       0     .72      .1       0   407.1    .045       0
     417     .05       0  618.18      .1       0  721.09      .1       0
Bank Sta=407.1,417
XS Rating Curve= 0 ,0
Exp/Cntr=0.3,0.1

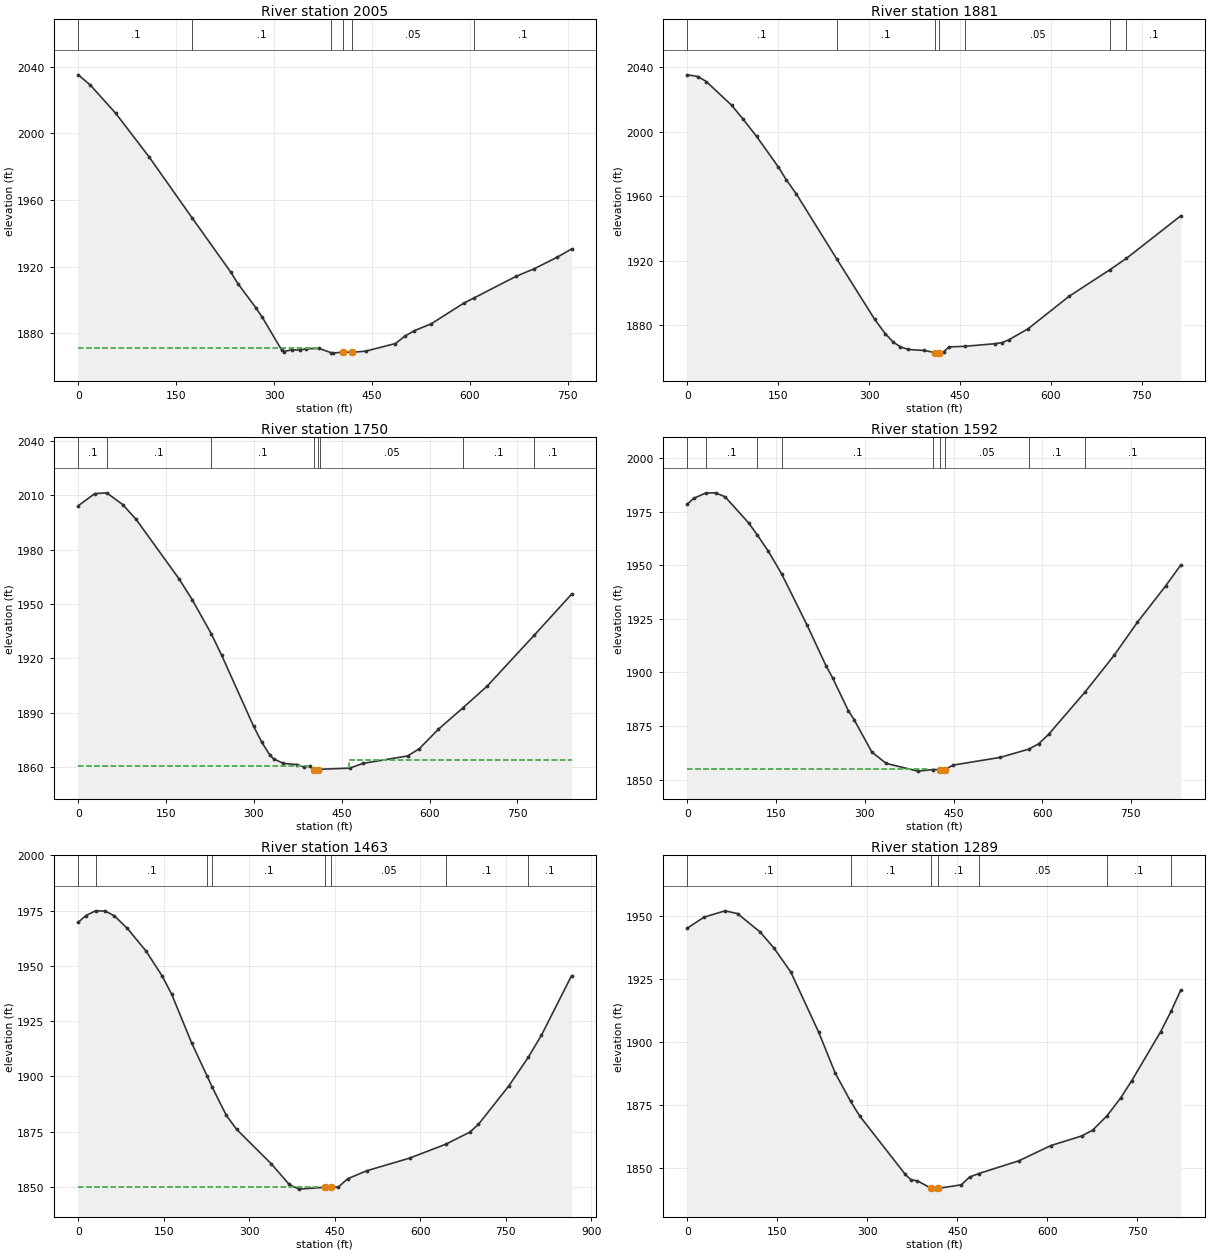
Type RM Length L Ch R = 1 ,2005    ,126.3,124,121.7
XS GIS Cut Line= 4
2433916.36310801584765.9341060932434166.18536676584590.442643345
2434346.33736293584536.3970444952434536.81183894584356.093910311
#Sta/Elev= 30
       0 2035.15    18.3 2029.12    57.4 2012.09   108.4 1986.01  174.771949.142
   233.3 1916.99   244.9 1909.73   272.4 1895.23   282.2 1889.53   311.6 1870.06
     315 1869.12   327.3 1870.15   339.8 1869.89   348.2 1870.74   369.1 1870.93
  387.191868.464     390 1868.15   406.21868.815   419.2 1868.64   440.1 1869.31
     486 1873.92   500.2 1878.28   514.4 1881.52     541  1885.8   590.7 1898.17
  606.271901.257   670.9 1914.27   698.3 1918.75     733 1925.55   755.7 1930.64
#Mann= 6 ,-1 , 0
       0      .1       0  174.77      .1       0  387.19     .05       0
   406.2    .045       0   419.2     .05       0  606.27      .1       0
#XS Ineff= 2 , 0
          369.29 1870.97
Permanent Ineff=
       F       F
Bank Sta=406.2,419.2
XS Rating Curve= 0 ,0
Exp/Cntr=0.3,0.1

Type RM Length L Ch R = 1 ,1881    ,133.1,130.9,128.4
XS GIS Cut Line= 3
     2433960.018      584874.0192434413.48492514 584615.00882464
2434613.14992863584401.472928632
#Sta/Elev= 30
       0 2035.23    17.6 2034.18    31.4    2031    72.9 2016.39    91.3 2008.03
   114.3 1997.02     150 1978.17   163.5 1970.02   180.1 1961.22  246.41 1921.17
     309 1883.76   326.6 1874.78     340 1869.46   351.6 1866.63   364.7 1864.95
   390.7 1864.32   408.7 1863.03   413.7 1862.68   416.1 1862.88   423.4 1863.64
   432.2 1866.53  458.51 1866.92   508.4 1868.54   519.7 1869.24   530.7 1870.93
   562.6  1877.8   630.2 1897.91  697.891914.464  724.591921.351   814.6  1947.8
#Mann= 7 ,-1 , 0
       0      .1       0  246.41      .1       0   408.7    .045       0
   416.1      .1       0  458.51     .05       0  697.89      .1       0
  724.59      .1       0
Bank Sta=408.7,416.1
XS Rating Curve= 0 ,0
Exp/Cntr=0.3,0.1

Type RM Length L Ch R = 1 ,1750    ,159,158.4,157.8
XS GIS Cut Line= 2
2434084.55163741585068.6008736692434685.38280038584478.199327865
#Sta/Elev= 30
       0 2004.16    28.1 2010.87    48.62011.314    76.2 2004.79    98.8 1996.71
   172.1 1963.91   194.5 1952.45  227.161933.632     245  1921.7   299.6 1882.48
   313.7 1873.65   326.7 1866.97   333.5 1864.61   350.5 1862.06   373.9 1861.45
   385.1  1860.1   395.2 1860.47     402 1858.48   406.6 1857.82   409.9 1858.39
  413.631858.866   463.6 1859.47   486.1 1862.07   562.6  1866.2   582.4 1870.18
     615 1880.91  656.971892.719   698.4 1904.74  778.651932.775   842.4 1955.39
#Mann= 8 ,-1 , 0
       0      .1       0    48.6      .1       0  227.16      .1       0
     402    .045       0   409.9      .1       0  413.63     .05       0
  656.97      .1       0  778.65      .1       0
#XS Ineff= 2 , 0
          393.87 1860.56  462.91         1863.85
Permanent Ineff=
       F       F
Bank Sta=402,409.9
XS Rating Curve= 0 ,0
Exp/Cntr=0.3,0.1

Type RM Length L Ch R = 1 ,1592    ,126.4,128.4,130.1
XS GIS Cut Line= 2
     2434220.342      585187.257     2434773.789      584562.893
#Sta/Elev= 30
       0 1978.48    10.3 1981.11   30.911983.646    47.7 1983.73    63.7 1981.88
   103.8 1969.62  118.391963.984   137.1 1956.37  159.141946.038   202.6 1921.91
   234.2 1903.17   245.5 1897.45   272.1 1882.12   281.8 1877.99   311.9 1862.84
     336 1857.54   389.7 1853.92  415.591854.671   427.1 1854.65   435.3 1854.65
   449.5 1856.74   528.7 1860.31  577.251864.177     594 1866.67     611 1871.12
  672.041890.701   721.5 1907.89   761.1 1923.41   808.6 1940.25   834.3 1950.04
#Mann= 9 ,-1 , 0
       0      .1       0   30.91      .1       0  118.39      .1       0
  159.14      .1       0  415.59     .05       0   427.1    .045       0
   435.3     .05       0  577.25      .1       0  672.04      .1       0
#XS Ineff= 2 , 0
          406.52 1854.87
Permanent Ineff=
       F       F
Bank Sta=427.1,435.3
XS Rating Curve= 0 ,0
Exp/Cntr=0.3,0.1

Type RM Length L Ch R = 1 ,1463    ,173.9,174.6,175.6
XS GIS Cut Line= 2
     2434248.793      585219.7982434937.06116489584695.709203452
#Sta/Elev= 30
       0 1969.69    13.2 1972.72   30.391974.891    47.6 1974.76    63.4 1972.64
    86.2 1966.93   119.2 1956.61   147.5 1945.28     164  1937.1   198.8 1915.18
  226.341899.989  235.071895.047   259.5 1882.44   277.6 1876.04   338.7 1860.36
     370 1851.07   387.2 1848.94   433.4  1849.8   443.61849.746   455.9 1849.85
   472.8 1853.67   505.8 1857.24     581 1862.97  644.42 1869.25   686.8 1874.74
   701.9 1878.29   755.4 1895.74  789.161908.589   812.4 1918.65   865.1 1945.51
#Mann= 8 ,-1 , 0
       0      .1       0   30.39      .1       0  226.34      .1       0
  235.07      .1       0   433.4    .045       0   443.6     .05       0
  644.42      .1       0  789.16      .1       0
#XS Ineff= 2 , 0
          421.21 1850.04
Permanent Ineff=
       F       F
Bank Sta=433.4,443.6
XS Rating Curve= 0 ,0
Exp/Cntr=0.3,0.1

Type RM Length L Ch R = 1 ,1289    ,181.2,203.7,179.8
XS GIS Cut Line= 2
     2434311.618      585317.976     2435017.181      584895.631
#Sta/Elev= 30
       0 1945.32    27.6 1949.64    62.7 1952.16    83.5 1951.07   121.5 1943.67
   144.1 1937.41   172.1 1927.96   218.7 1904.03   246.6 1887.63  271.981876.542
   287.2 1870.69   363.2 1847.52   372.5  1845.4   383.5 1844.97   406.21841.995
   412.6 1841.67   418.31841.994   456.4 1843.38   470.4 1846.47  485.761847.863
   552.6 1852.93   605.6 1858.95   657.6  1862.8   675.5 1865.11  699.531870.828
   722.1 1877.86   740.7 1884.75   788.8 1904.17  806.421912.402   822.3  1920.7
#Mann= 7 ,-1 , 0
       0      .1       0  271.98      .1       0   406.2    .045       0
   418.3      .1       0  485.76     .05       0  699.53      .1       0
  806.42      .1       0
Bank Sta=406.2,418.3
XS Rating Curve= 0 ,0
Exp/Cntr=0.3,0.1

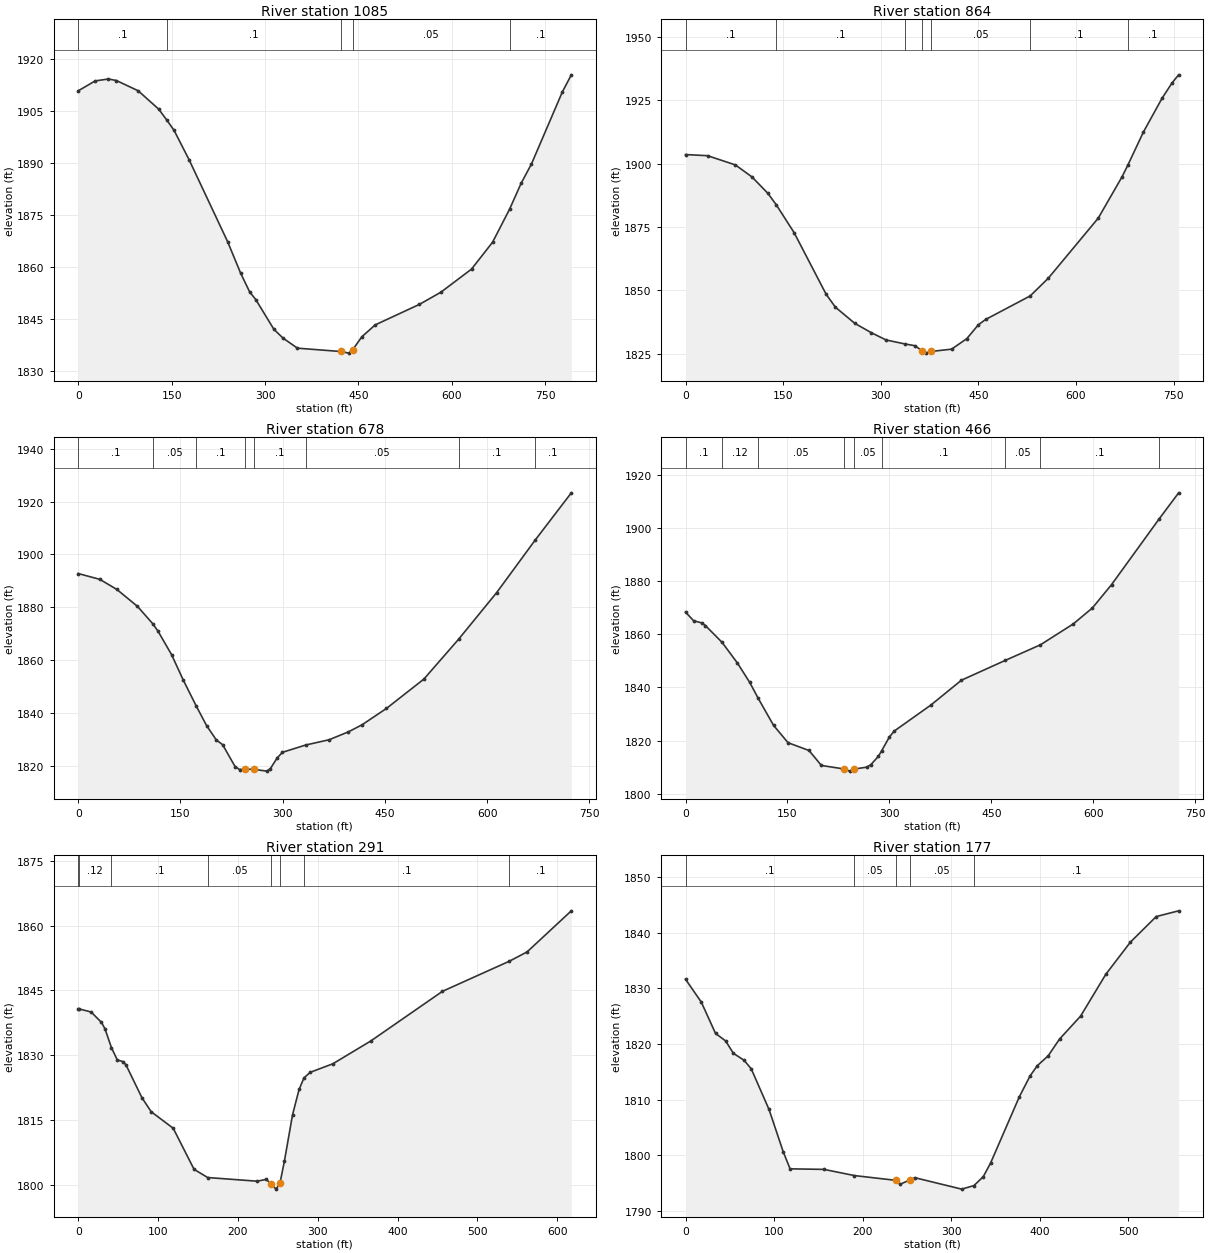
Type RM Length L Ch R = 1 ,1085    ,199,221.3,198.2
XS GIS Cut Line= 2
2434460.87631848585463.184179788 2435111.9306705585012.298712394
#Sta/Elev= 30
       0 1910.73    27.2 1913.59    48.5 1914.15    61.3 1913.71    96.3 1910.75
   129.4 1905.43   142.51902.239   153.9 1899.35     178 1890.88     240  1867.2
   260.7 1858.19   275.3 1852.73   285.1 1850.53   314.2 1841.95   328.8 1839.41
   352.1 1836.49   421.3 1835.53   434.9 1835.06   440.7 1836.01   455.6  1839.8
     477 1843.21   547.8 1849.11   582.4 1852.63   631.6  1859.3   665.4 1867.05
  692.661876.556   711.4  1884.1   727.8  1889.6   777.5 1910.42   791.9 1915.35
#Mann= 5 ,-1 , 0
       0      .1       0   142.5      .1       0   421.3    .045       0
   440.7     .05       0  692.66      .1       0
Bank Sta=421.3,440.7
XS Rating Curve= 0 ,0
Exp/Cntr(USF)=0,0
Exp/Cntr=0.3,0.1

Type RM Length L Ch R = 1 ,864     ,186.1,186,187.4
XS GIS Cut Line= 2
 2434620.6070446585612.8053662772435211.00415885585137.657003777
#Sta/Elev= 30
       0 1903.64    33.9 1903.19    76.7 1899.55   102.3 1894.78   126.6 1888.33
   139.61883.762   166.8 1872.86   216.1  1848.5   230.3 1843.41   260.1 1837.02
   285.7  1833.3   308.2 1830.46  336.871828.898   352.5 1828.19     364 1826.11
   369.7 1825.26   377.2 1825.91   408.9 1826.83   432.3 1830.98     450 1836.44
   461.3 1838.56  529.751847.849   557.5 1854.83   634.3 1878.56   670.8 1894.84
  679.591899.379   703.7 1912.56   732.4  1925.9     748 1932.04   757.8 1935.11
#Mann= 7 ,-1 , 0
       0      .1       0   139.6      .1       0  336.87     .05       0
     364    .045       0   377.2     .05       0  529.75      .1       0
  679.59      .1       0
Bank Sta=364,377.2
XS Rating Curve= 0 ,0
Exp/Cntr(USF)=0,0
Exp/Cntr=0.3,0.1

Type RM Length L Ch R = 1 ,678     ,212,212,210.8
XS GIS Cut Line= 2
2434733.83388843585705.8131308522435312.09955513585271.102926862
#Sta/Elev= 30
       0 1892.73    31.8 1890.52    56.8 1886.69    86.8 1880.33  109.191873.779
   116.8 1871.02   136.9 1862.06     154 1852.46  173.111842.594   188.3 1835.17
   202.6 1829.72   211.9 1827.91   230.1 1819.65   236.8  1818.5   245.4 1818.65
   257.5 1818.58   276.9 1817.91   281.9 1818.83   291.9 1822.92   299.7 1825.04
  333.591827.787   368.2  1829.8   396.5  1832.8   416.5 1835.47   452.1 1841.63
   507.1 1852.76  557.981867.831   613.9 1885.52  670.181905.334   723.4 1923.29
#Mann= 8 ,-1 , 0
       0      .1       0  109.19     .05       0  173.11      .1       0
   245.4    .045       0   257.5      .1       0  333.59     .05       0
  557.98      .1       0  670.18      .1       0
Bank Sta=245.4,257.5
XS Rating Curve= 0 ,0
Exp/Cntr(USF)=0,0
Exp/Cntr=0.3,0.1

Type RM Length L Ch R = 1 ,466     ,175.6,174.6,174.2
XS GIS Cut Line= 3
2434909.73987795 585851.390501492435304.01192343585505.644246224
2435326.25291061585305.475361596
#Sta/Elev= 30
       0 1868.36    11.9  1865.1    24.1 1864.27    29.3 1863.29   53.841856.959
    76.4  1849.2    94.5 1841.92  106.971835.938   129.6 1825.76   150.9 1819.24
   181.8 1816.31     200 1810.68   233.41809.362   241.8 1808.55   247.5  1809.3
   266.7 1810.04   272.8 1810.99   283.9 1814.12   288.9 1816.29   299.8 1821.28
     307 1823.58   360.9 1833.35   406.2 1842.75  470.821850.205  522.481856.056
   570.8 1863.91   598.9 1869.91   627.1 1878.69  696.741903.256   725.8 1913.19
#Mann= 9 ,-1 , 0
       0      .1       0   53.84     .12       0  106.97     .05       0
   233.4    .045       0   247.5     .05       0   288.9      .1       0
  470.82     .05       0  522.48      .1       0  696.74      .1       0
Bank Sta=233.4,247.5
XS Rating Curve= 0 ,0
Exp/Cntr(USF)=0,0
Exp/Cntr=0.3,0.1

Type RM Length L Ch R = 1 ,291     ,117.3,114.2,112.1
XS GIS Cut Line= 3
2435041.16389311585970.6830690972435271.66139662585750.295105213
2435328.27481853585457.118456011
#Sta/Elev= 30
       0 1840.76      .61840.756    16.2 1840.01    29.1 1837.61    33.5 1836.13
   41.651831.742    48.9 1828.92    56.7 1828.47    60.2 1827.62    79.8 1820.15
    91.4  1816.9     119 1813.06   145.1 1803.54  162.171801.644   224.1  1800.8
   235.6 1801.22   241.9 1800.09   247.7 1798.96   252.6 1800.28   258.3 1805.53
   268.4 1816.19   276.6 1822.06  282.69 1824.73   290.5 1826.03   318.9 1828.01
   366.5 1833.31   456.1  1844.8  539.991851.789   562.1 1853.94   617.5 1863.46
#Mann= 8 ,-1 , 0
       0      .1       0      .6     .12       0   41.65      .1       0
  162.17     .05       0   241.9    .045       0   252.6     .05       0
  282.69      .1       0  539.99      .1       0
Bank Sta=241.9,252.6
XS Rating Curve= 0 ,0
Exp/Cntr(USF)=0,0
Exp/Cntr=0.3,0.1

Type RM Length L Ch R = 1 ,177     ,110.5,113.4,121.4
XS GIS Cut Line= 4
2435073.51441992 585982.81451665 2435190.7850796585996.967872128
2435306.03383135 585851.390501492435352.53771364 585602.69582665
#Sta/Elev= 30
       0 1831.65    17.8 1827.54    33.9  1821.9    45.3 1820.55      54 1818.33
    66.1 1817.07    74.2 1815.54    94.3 1808.22   110.4 1800.58   118.1 1797.54
   156.4 1797.44  190.651796.331   237.21795.474   242.4 1794.77   253.3 1795.54
   258.9 1795.95   311.8 1793.89  325.691794.527   336.2 1796.13   344.4 1798.56
   376.9 1810.49   389.1 1814.27   397.2 1816.09   409.5 1817.87   422.3 1820.88
   446.1 1825.01   474.6 1832.54   502.4 1838.33   531.5 1842.92   556.8 1843.95
#Mann= 5 ,-1 , 0
       0      .1       0  190.65     .05       0   237.2    .045       0
   253.3     .05       0  325.69      .1       0
Bank Sta=237.2,253.3
XS Rating Curve= 0 ,0
Exp/Cntr(USF)=0,0
Exp/Cntr=0.3,0.1

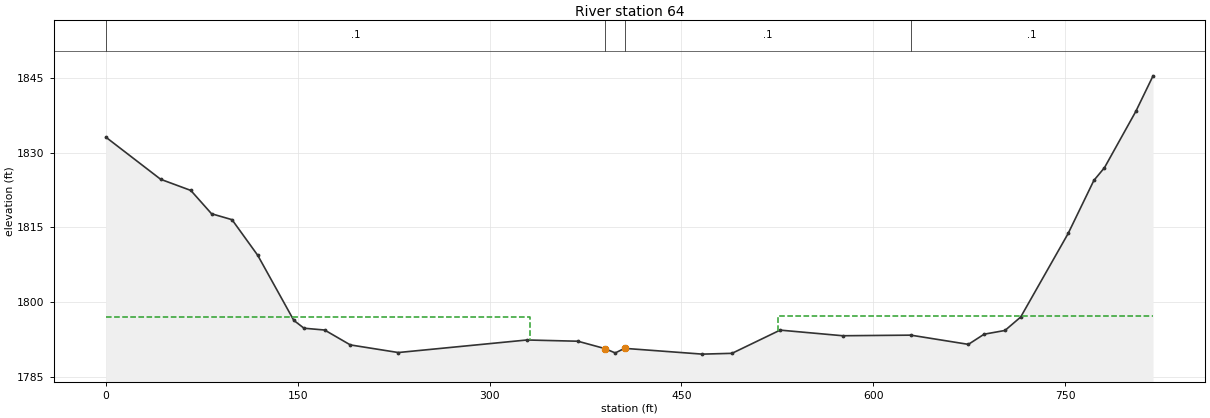
Type RM Length L Ch R = 1 ,64      ,,,
XS GIS Cut Line= 4
2435036.80492221585997.5539998082435243.36900945586020.815721345
2435455.51590987585835.6524179122435524.37060562585513.710191842
#Sta/Elev= 30
       0  1833.1    42.8 1824.65    66.4 1822.41    82.6 1817.73    98.6 1816.54
   118.7 1809.39   146.9 1796.33   154.9 1794.75     171 1794.39   191.1  1791.4
   228.6 1789.87   329.2 1792.39     369 1792.14     390 1790.67   398.2 1789.79
   405.5 1790.71   466.3 1789.55   489.5 1789.71   527.1 1794.37   576.1 1793.24
   629.3 1793.36   674.3 1791.51   686.6 1793.55   702.9  1794.3   715.2    1797
   752.3 1813.77   772.4 1824.42   780.7 1826.98   805.2 1838.28818.6807 1845.42
#Mann= 4 ,-1 , 0
       0      .1       0     390    .045       0   405.5      .1       0
   629.3      .1       0
#XS Ineff= 2 , 0
          331.89 1796.92  525.13         1797.15
Permanent Ineff=
       F       F
Bank Sta=390,405.5
XS Rating Curve= 0 ,0
Exp/Cntr(USF)=0,0
Exp/Cntr=0.3,0.1
LCMann Table=0

Chan Stop Cuts=-1
Use User Specified Reach Order=0
Composite Channel Slope=5